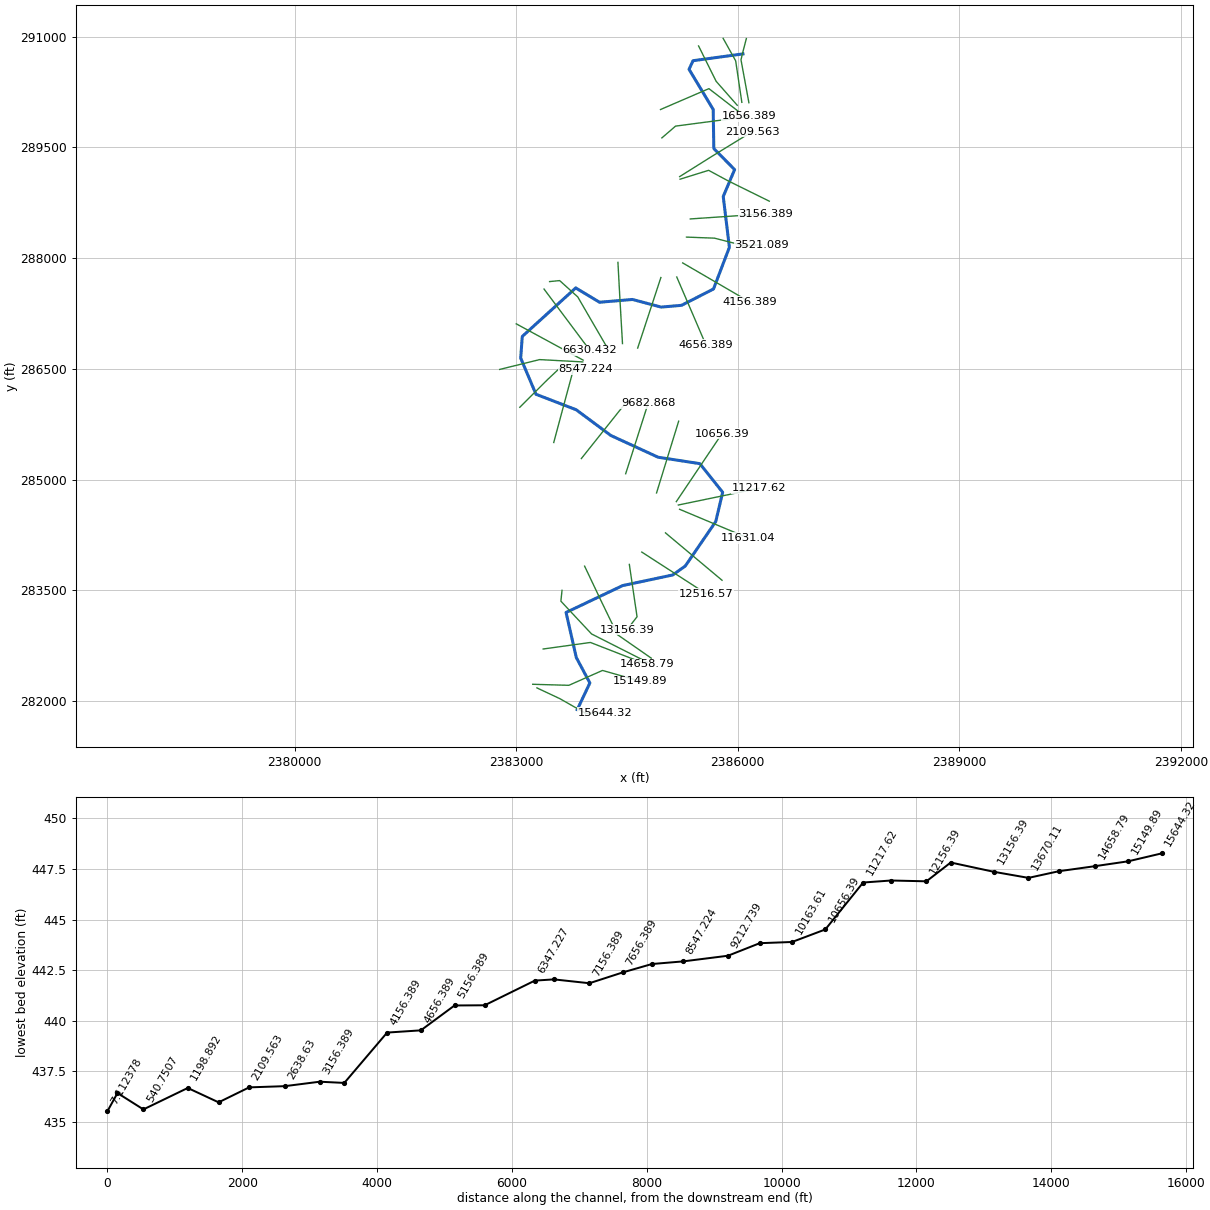
--- OpequonCreek.prj (project) ---

Proj Title=OpequonCreek
Current Plan=p01
Default Exp/Contr=0.3,0.1
English Units
Geom File=g01
Flow File=f01
Plan File=p01
Y Axis Title=Elevation
X Axis Title(PF)=Main Channel Distance
X Axis Title(XS)=Station
BEGIN DESCRIPTION:
END DESCRIPTION:
DSS Export Rating Curves= 0
DSS Export Rating Curve Sorted= 0
DSS Export Volume Flow Curves= 0
DXF OffsetX= 0
DXF OffsetY= 0
DXF ScaleX= 1
DXF ScaleY= 10

--- OpequonCreek.p01 (plan) ---

Plan Title=Plan 01
Program Version=4.10
Short Identifier=Plan 01
Geom File=g01
Flow File=f01
Subcritical Flow
K Sum by GR= 0
Std Step Tol= 0.01
Critical Tol= 0.01
Num of Std Step Trials= 20
Max Error Tol= 0.3
Flow Tol Ratio= 0.001
Split Flow NTrial= 30
Split Flow Tol= 0.02
Split Flow Ratio= 0.02
Log Output Level= 0
Friction Slope Method= 1
Unsteady Friction Slope Method= 2
Unsteady Bridges Friction Slope Method= 1
Parabolic Critical Depth
Global Vel Dist= 0 , 0 , 0
Global Log Level= 0
CheckData=True
Encroach Param=-1 ,0,0, 0
Computation Interval=1HOUR
Output Interval=1HOUR
Run HTab= 0
Run UNet= 0
Run PostProcess= 0
Run WQNet= 0
UNET Theta= 1
UNET Theta Warmup= 1
UNET ZTol= 0.02
UNET ZSATol= 0.05
UNET MxIter= 20
UNET MaxInSteps= 0
UNET DtIC= 0
UNET DtMin= 0
UNET MaxCRTS= 20
UNET WFStab= 2
UNET SFStab= 1
UNET WFX= 1
UNET SFX= 1
UNET DSS MLevel= 4
UNET DZMax Abort= 100
UNET Convert EG Bridges= 0
UNET Use Existing IB Tables=-1
UNET Froude Reduction=False
UNET Froude Limit= 1
UNET Froude Power= 10
UNET Time Slicing=0,0, 5
UNET Junction Losses=0
Instantaneous Interval=1HOUR
Write IC File= 0
Write IC File at Sim End=0
Echo Input=False
Echo Parameters=False
Echo Output=False
Write Detailed= 0
WQ AD Non Conservative
WQ ULTIMATE=-1
WQ Max Comp Step=1HOUR
WQ Output Interval=15MIN
WQ Output Selected Increments= 0
WQ Output face flow=0
WQ Output face velocity=0
WQ Output face area=0
WQ Output face dispersion=0
WQ Output cell volume=0
WQ Output cell surface area=0
WQ Output cell continuity=0
WQ Output cumulative cell continuity=0
WQ Output face conc=0
WQ Output face dconc_dx=0
WQ Output face courant=0
WQ Output face peclet=0
WQ Output face adv mass=0
WQ Output face disp mass=0
WQ Output cell mass=0
WQ Output cell source sink temp=0
WQ Output cell source sink nsm=0
WQ Output MaxMinRange=-1
WQ Daily Max Min Mean=-1
WQ Daily Range=0
WQ Daily Time=0
WQ Create Restart=0
WQ Fixed Restart=0
WQ System Summary=0
WQ Use Fixed Temperature=0
Sorting and Armoring Iterations= 10
XS Update Threshold= 0.02
Hydraulics Update Threshold= 0.02
Energy Slope Method= 1
Volume Change Method= 0
XS Weighting Method= 0
Number of US Weighted Cross Sections= 1
Number of DS Weighted Cross Sections= 1
Upstream XS Weight=0.25
Main XS Weight=0.5
Downstream XS Weight=0.25
Number of DS XS's Weighted with US Boundary= 1
Upstream Boundary Weight= 1
Weight of XSs Associated with US Boundary= 0
Number of US XS's Weighted with DS Boundary= 1
Downstream Boundary Weight= 0.5
Weight of XSs Associated with DS Boundary= 0.5
Sediment Output Level= 4
Mass or Volume Output= 0
Output Increment Type= 1
Profile and TS Output Increment= 10
XS Output Flag= 0
XS Output Increment= 10
Disregard all LS=0
Disregard all Conn=0
Disregard all Breaches=0
Disregard all Pumps=0

--- OpequonCreek.f01 (steady flow) ---

Flow Title=OpequonCreek
Program Version=4.10
Number of Profiles= 1
Profile Names=PF 1
River Rch & RM=OpequonCreek,Reach1          ,15644.32
   21484
River Rch & RM=OpequonCreek,Reach1          ,6347.227
   22248
Boundary for River Rch & Prof#=OpequonCreek,Reach1          , 1
Up Type= 0
Dn Type= 1
Dn Known WS=452.5
DSS Import GetInterval= 0
DSS Import GetPeak= 0
DSS Import FillOption= 0

--- OpequonCreek.g01 (geometry) ---

Geom Title=OpequonCreek
Program Version=4.10

River Reach=OpequonCreek    ,Reach1
Reach XY= 30
2383826.17977361281882.7540716832383997.33297461282245.636876106
2383813.47868353282589.3868447692383674.93696585283199.803602934
2384441.08307137283563.8661950232385119.42489052283707.572600514
2385289.02100803283828.2334484312385702.06381711 284430.92351602
2385795.81395769284827.2777101842385486.95958853 285215.29858768
2384921.85540378285302.2777444422384281.75136903 285596.54848136
2383811.43898945285945.5067729352383267.29178378286155.075907603
2383060.39718445286645.5066852722383081.88073727286937.823685944
2383805.70967019287595.5067537732384127.58468261287401.235816851
2384574.45977311287438.736069933 2384962.4806506287335.610948101
2385239.04308961287359.5692335222385671.85554419287580.923449606
2385886.87283069288145.3130688522385803.53966403288833.160118356
2385957.55051085289197.6229721012385676.10881652289483.507242858
2385667.49794136290012.1183903522385340.41460602 290555.86861518
2385394.58116436290672.535048515 2386069.9393937  290764.5489721

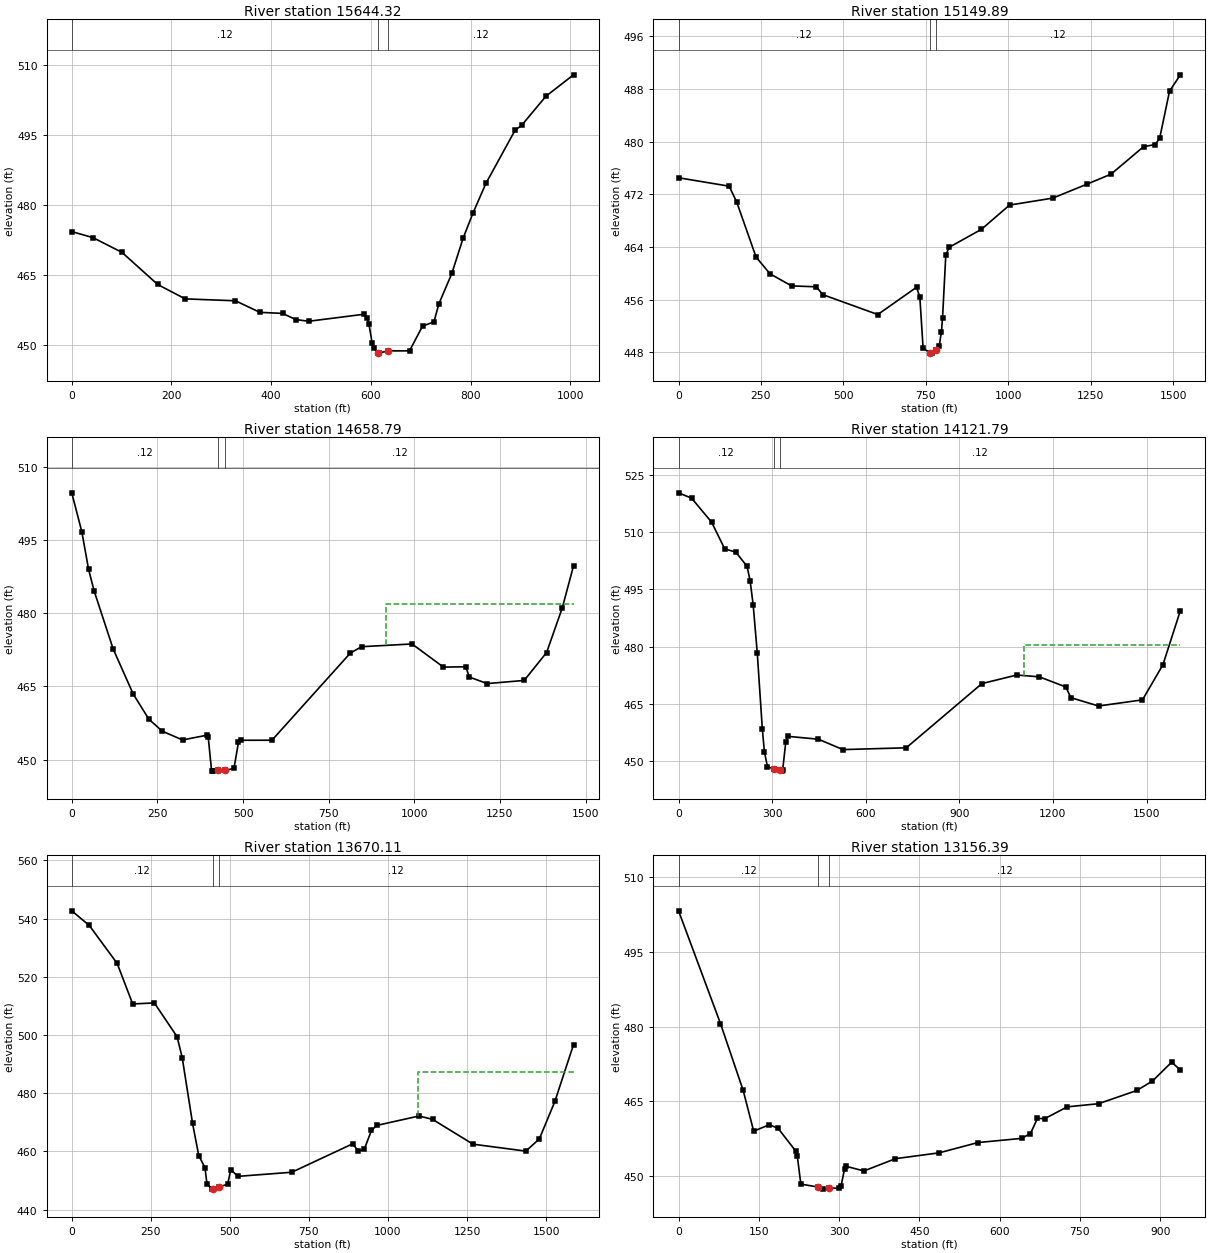
Type RM Length L Ch R = 1 ,15644.32,461.34,494.43,521.13
Node Name=964
XS GIS Cut Line= 5
2383280.51157361 282178.26397936 2383592.3593751 282031.77477102
2383836.16367753281892.9676339332383941.08735219 281833.23054868
 2384201.2935247281839.382767349
#Sta/Elev= 30
       0  474.28   42.25     473  100.76  469.83  172.27  462.96  227.53  459.88
  328.29  459.47  377.16     457  422.83  456.77  448.93  455.46  475.03  455.09
  585.94  456.59  592.47  455.82  595.73  454.59  602.25  450.49  605.52  449.45
  614.09  448.39   615.3  448.27  634.26  448.75   677.3  448.76  703.41  454.06
  726.25  454.95  736.04   458.8  762.09  465.32  784.87  472.91  804.39  478.22
  830.42  484.59  888.98  495.98  901.99  497.01   950.8  503.25 1006.11  507.83
#Mann= 3 , 0 , 0
       0     .12       0  614.09    .045       0  634.26     .12       0
Bank Sta=614.09,634.26
XS Rating Curve= 0 ,0
Exp/Cntr=0.3,0.1

Type RM Length L Ch R = 1 ,15149.89,498.37,491.1,481.49
Node Name=965
XS GIS Cut Line= 5
2383223.10322386282227.1936715252383712.70755962282213.257347688
2383973.10205194282328.4706999362384167.96714778282414.690343767
2384682.10982028282268.612880021
#Sta/Elev= 30
       0  474.51  153.47  473.23  176.33  470.83  235.11  462.47  277.55  459.92
  342.86  458.09  417.96  457.95  437.56  456.76  604.36  453.74  722.18  457.89
     732  456.34  741.82  448.63  761.24  447.97     768  447.88  781.92  448.34
  790.94  449.03   797.5  451.16  800.77   453.2  810.61  462.72  820.44  463.94
  918.79  466.68 1004.03  470.36  1135.2  471.42 1240.13  473.56 1312.27  475.07
 1410.64  479.23 1446.71  479.56 1459.82   480.6 1489.33  487.66 1522.12  490.14
#Mann= 3 , 0 , 0
       0     .12       0  761.24    .045       0  781.92     .12       0
Bank Sta=761.24,781.92
XS Rating Curve= 0 ,0
Exp/Cntr=0.3,0.1

Type RM Length L Ch R = 1 ,14658.79,564.45,537,506.18
Node Name=966
XS GIS Cut Line= 4
2383364.74992219 282705.099867942383863.06782319 282774.02230227
2384005.07803786282793.6636671872384767.83012128282496.477581769
#Sta/Elev= 30
       0  504.63    29.4  496.66      49  489.02   65.33  484.54  120.87  472.66
  179.66   463.4   225.4  458.25   264.6  455.81   323.4  454.03  395.26     455
  398.53  454.57  408.33  447.65   411.6  447.64  427.75   447.9  448.46  447.78
  473.66  448.22  486.73  453.52  493.26  453.96  584.52  453.97  813.42  471.82
  846.16  473.12  993.51  473.68  1085.2  468.94 1150.68  469.01 1160.51  466.91
  1212.9  465.57 1320.95  466.21 1386.44  471.93 1432.28  481.09 1465.02  489.68
#Mann= 3 , 0 , 0
       0     .12       0  427.75    .045       0  448.46     .12       0
#XS Ineff= 2 , 0
                          918.25          481.89
Permanent Ineff=
       F       F
Bank Sta=427.75,448.46
XS Rating Curve= 0 ,0
Exp/Cntr=0.3,0.1

Type RM Length L Ch R = 1 ,14121.79,460.67,451.68,441.62
Node Name=967
XS GIS Cut Line= 5
2383620.10866344283499.8066118512383604.85278845283352.693717107
2383711.77416253283238.4678956872384020.42085494282908.734959349
2384780.85109261282523.604167938
#Sta/Elev= 30
       0  520.29    41.8  518.89   106.1  512.58   147.9  505.62  183.76  504.74
  219.61  501.03  229.39  497.24  239.17  490.96  252.21  478.43  268.51  458.46
  275.03  452.53   284.8   448.6   304.5  447.95  324.18  447.59  330.54  447.39
  333.82  447.77  343.64  454.98  350.18   456.5  448.37  455.75  526.91  453.03
  729.83   453.5  972.39  470.32 1083.85  472.56 1155.98   472.1 1241.22  469.45
 1257.61  466.63 1346.13  464.45  1487.1  466.06 1552.67  475.26 1608.41  489.41
#Mann= 3 , 0 , 0
       0     .12       0   304.5    .045       0  324.18     .12       0
#XS Ineff= 2 , 0
                         1106.42          480.42
Permanent Ineff=
       F       F
Bank Sta=304.5,324.18
XS Rating Curve= 0 ,0
Exp/Cntr=0.3,0.1

Type RM Length L Ch R = 1 ,13670.11,520.1,513.72,502.13
Node Name=968
XS GIS Cut Line= 4
 2383925.9121857283827.5585810242384140.22967044283376.308499277
2384371.10256827282899.2005296052384828.59410736 282581.11291118
#Sta/Elev= 30
       0  542.68   55.51  537.64  143.66  524.61  192.64  510.69  261.21  511.03
  333.04  499.44  349.36  492.22  382.01  469.67  401.61  458.59   421.2  454.47
  427.73  448.77  444.05  447.06  445.86  447.06  465.81   447.8  493.03  448.76
  502.83  453.71  525.73  451.45  695.87  452.86   888.9  462.66  905.26  460.19
  924.89  460.68   947.8  467.25  964.15  468.94 1098.42  472.19 1141.03  471.03
 1268.86   462.5 1436.02  460.12 1478.63   464.3  1527.8  477.18  1586.8  496.72
#Mann= 3 , 0 , 0
       0     .12       0  445.86    .045       0  465.81     .12       0
#XS Ineff= 2 , 0
                         1096.02          487.26
Permanent Ineff=
       F       F
Bank Sta=445.86,465.81
XS Rating Curve= 0 ,0
Exp/Cntr=0.3,0.1

Type RM Length L Ch R = 1 ,13156.39,609.14,639.82,662.96
Node Name=969
XS GIS Cut Line= 4
2384531.88767977283850.7498075962384571.35971369 283582.68571119
2384636.28937386283141.7348214392384500.75093102282967.109842598
#Sta/Elev= 30
       0   503.3   78.35  480.64  120.79  467.19  140.37  459.01  169.75  460.31
  186.08  459.57  218.72  455.05  221.99  453.93  228.52  448.37  261.19  447.78
  270.73  447.36  281.07  447.62  300.45  447.51  303.73  448.01  310.28  451.48
  313.56  451.94  346.33  451.01  405.32  453.48  487.25  454.66  559.35  456.72
  641.28  457.56  657.67  458.54  670.78   461.6  683.89   461.5  726.41   463.9
  784.93  464.53  856.44  467.19   885.7  469.09  921.46  472.87  937.71  471.31
#Mann= 3 , 0 , 0
       0     .12       0  261.19    .045       0  281.07     .12       0
Bank Sta=261.19,281.07
XS Rating Curve= 0 ,0
Exp/Cntr=0.3,0.1

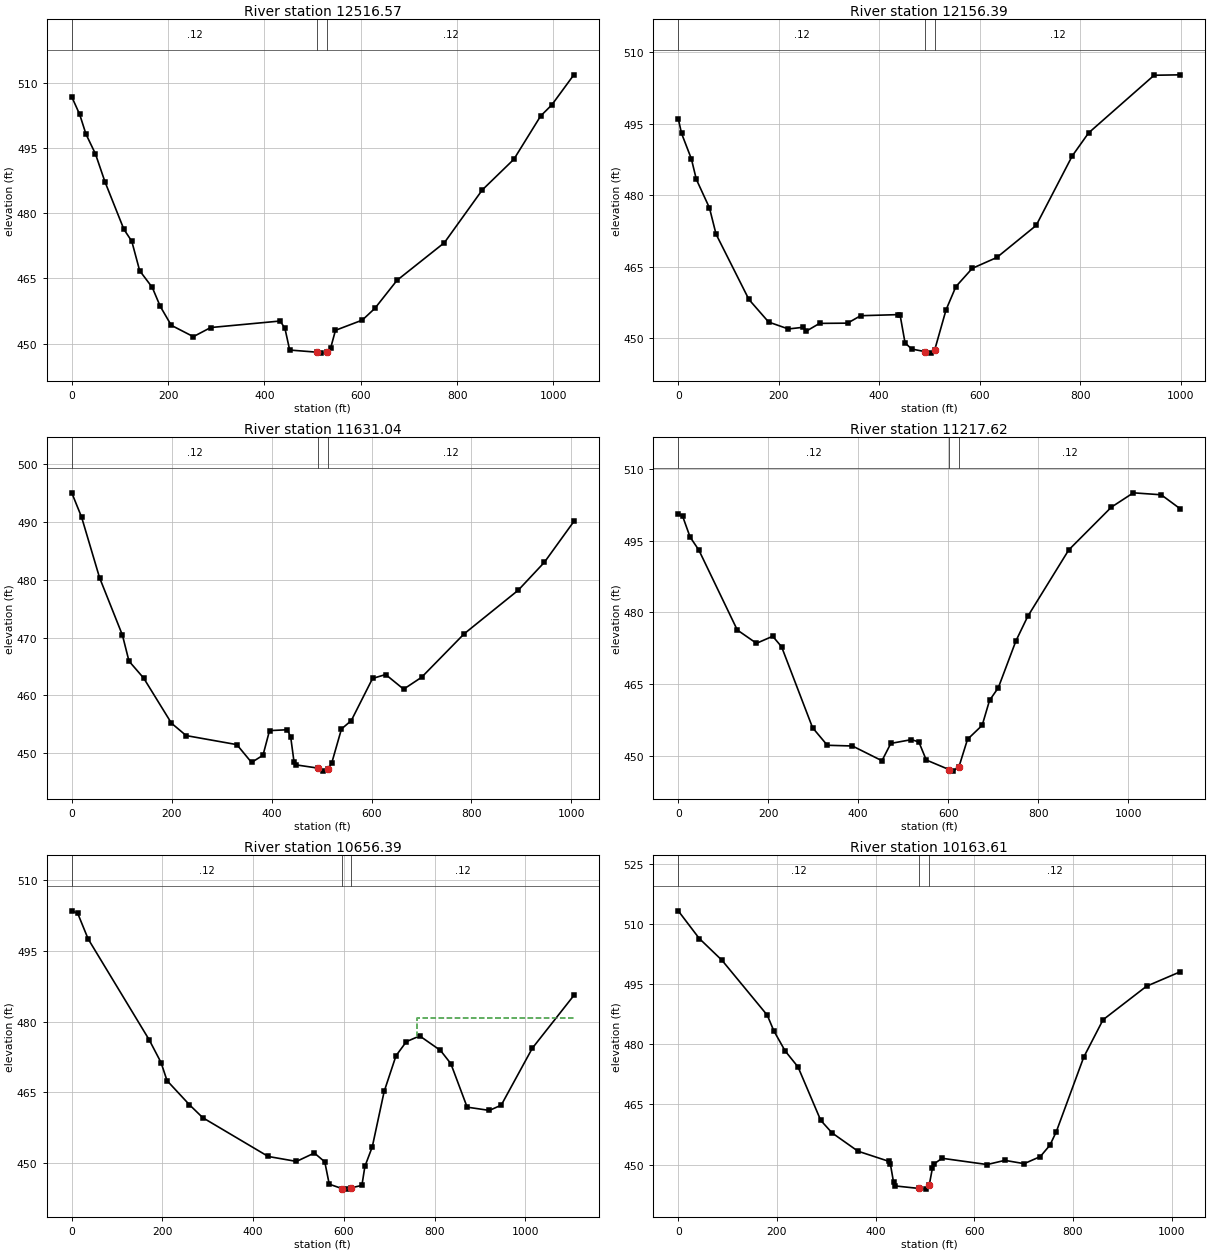
Type RM Length L Ch R = 1 ,12516.57,363.09,360.18,355.17
Node Name=970
XS GIS Cut Line= 3
2384700.44246078284017.9010481092385121.60992552283745.571212187
2385575.73368919283451.932035685
#Sta/Elev= 30
       0  506.79   16.39  502.77    29.5  498.22   49.17  493.67   68.84  487.27
  108.18  476.32  124.57  473.57  140.96  466.79  167.18  462.93  183.57  458.61
  206.52  454.23  252.41  451.61  288.47  453.71   432.7  455.21  442.54  453.51
  452.37  448.53   509.9  448.03  517.89  447.82  530.13  447.99   537.6  449.04
  547.43  453.07  603.15  455.42  629.37  458.14  675.25  464.58  773.58  473.24
  852.24  485.38  917.79  492.43   973.5  502.41  996.45  504.93 1042.33  511.87
#Mann= 3 , 0 , 0
       0     .12       0   509.9    .045       0  530.13     .12       0
Bank Sta=509.9,530.13
XS Rating Curve= 0 ,0
Exp/Cntr=0.3,0.1

Type RM Length L Ch R = 1 ,12156.39,516.16,525.35,534.14
Node Name=971
XS GIS Cut Line= 3
2385021.01924744  284277.90840212385404.64413635283956.505173519
2385786.98687561283636.175761685
#Sta/Elev= 30
       0  496.09    6.54  493.01   26.17  487.64   35.98  483.36   62.15  477.36
   75.23  471.86  140.65  458.15  179.91  453.41  219.16  451.96   248.6  452.31
  255.14  451.52  281.31  453.13  336.92  453.18  363.08  454.74  438.32  454.97
  441.59  454.86   451.4  449.05  464.49  447.75  490.46  447.22  503.73  446.89
  510.48  447.58  533.07  455.99  552.63  460.85  585.23  464.68  634.13  466.96
  712.37  473.68   784.1  488.25   816.7  493.09   947.1  505.19  999.26  505.28
#Mann= 3 , 0 , 0
       0     .12       0  490.46    .045       0  510.48     .12       0
Bank Sta=490.46,510.48
XS Rating Curve= 0 ,0
Exp/Cntr=0.3,0.1

Type RM Length L Ch R = 1 ,11631.04,389.45,413.42,427.99
Node Name=972
XS GIS Cut Line= 3
2385212.53100352284597.359862939 2385674.0189257284403.653229356
2386139.16661744284208.410509601
#Sta/Elev= 30
       0  495.01   19.63  490.82   55.61  480.35  101.41  470.42  114.49  465.94
  143.93     463  199.54  455.21  228.98  453.07  330.39  451.51  359.83  448.43
  382.73  449.67  395.81  453.93   431.8  454.08  438.34  452.74  444.88  448.52
  448.15  448.02  492.13  447.46  503.77  446.93  512.47  447.31  520.15  448.27
   539.8  454.21  559.46  455.66  602.04  462.94  628.25  463.62  664.28  461.09
  700.31  463.15  785.48  470.66  893.58  478.18  945.99  483.01 1004.95  490.06
#Mann= 3 , 0 , 0
       0     .12       0  492.13    .045       0  512.47     .12       0
Bank Sta=492.13,512.47
XS Rating Curve= 0 ,0
Exp/Cntr=0.3,0.1

Type RM Length L Ch R = 1 ,11217.62,535.99,561.24,579.43
Node Name=973
XS GIS Cut Line= 3
2385195.57270411284655.1592880192385799.51080069284780.330297515
 2386288.1397447284881.602732763
#Sta/Elev= 30
       0  500.59    9.84  500.05   26.25  495.74   45.93  492.98  131.23  476.31
  173.88  473.53  209.97     475  229.65  472.81  298.54   455.9  331.35  452.23
  387.12  452.08  452.74     449  472.42  452.62  518.35  453.41  534.76  452.92
  551.16  449.16  602.43  447.13  610.21  446.83  623.66  447.68  642.86  453.47
  675.48   456.4  691.79   461.6  711.36  464.26   750.5  474.04  776.59  479.13
  867.91  493.04  962.49  501.96 1011.42  504.96 1073.39  504.55 1115.79  501.61
#Mann= 3 , 0 , 0
       0     .12       0  602.43    .045       0  623.66     .12       0
Bank Sta=602.43,623.66
XS Rating Curve= 0 ,0
Exp/Cntr=0.3,0.1

Type RM Length L Ch R = 1 ,10656.39,482.17,492.77,500.43
Node Name=974
XS GIS Cut Line= 3
 2385168.1478902284701.1067026852385506.65869612285204.869474679
2385785.44160311 285619.74594152
#Sta/Elev= 30
       0  503.48   13.12  502.94   36.09  497.52   170.6  476.16  196.84  471.32
  209.97   467.5  259.18  462.41   288.7  459.65  433.05  451.43  495.39  450.38
  534.76  452.16  557.72  450.29  567.56  445.56  595.92  444.62  607.31  444.51
  615.86  444.78   639.6  445.31  646.14  449.32  662.47  453.48  688.61   465.2
  714.74  472.77  737.61  475.76  767.01  476.97  812.75   473.9  835.62   471.1
  871.55  461.88  920.56  461.19  946.69   462.3  1015.3  474.38 1106.77  485.55
#Mann= 3 , 0 , 0
       0     .12       0  595.92    .045       0  615.86     .12       0
#XS Ineff= 2 , 0
                          760.86          480.81
Permanent Ineff=
       F       F
Bank Sta=595.92,615.86
XS Rating Curve= 0 ,0
Exp/Cntr=0.3,0.1

Type RM Length L Ch R = 1 ,10163.61,481.21,480.75,479.96
Node Name=975
XS GIS Cut Line= 3
2384900.21568328284818.3567962652385052.90960361285313.667813525
2385199.92374527285790.553670764
#Sta/Elev= 30
       0  513.27   42.65  506.37   88.57  500.95  180.43  487.25  193.55  483.39
  216.51  478.36  242.75  474.34  288.68  461.05  311.64  457.91  364.13  453.35
  426.46  450.83  429.74  450.22   436.3  445.61  439.58  444.69  487.66  444.06
  501.91  443.89  508.47  444.83  515.03  449.12  518.31  450.18  534.62  451.58
  625.95  450.02  661.83  451.06  700.97  450.24  733.58     452  753.15  454.84
   766.2  458.25  821.65  476.79  860.79  486.11  948.85  494.47 1017.35  498.08
#Mann= 3 , 0 , 0
       0     .12       0  487.66    .045       0  508.47     .12       0
Bank Sta=487.66,508.47
XS Rating Curve= 0 ,0
Exp/Cntr=0.3,0.1

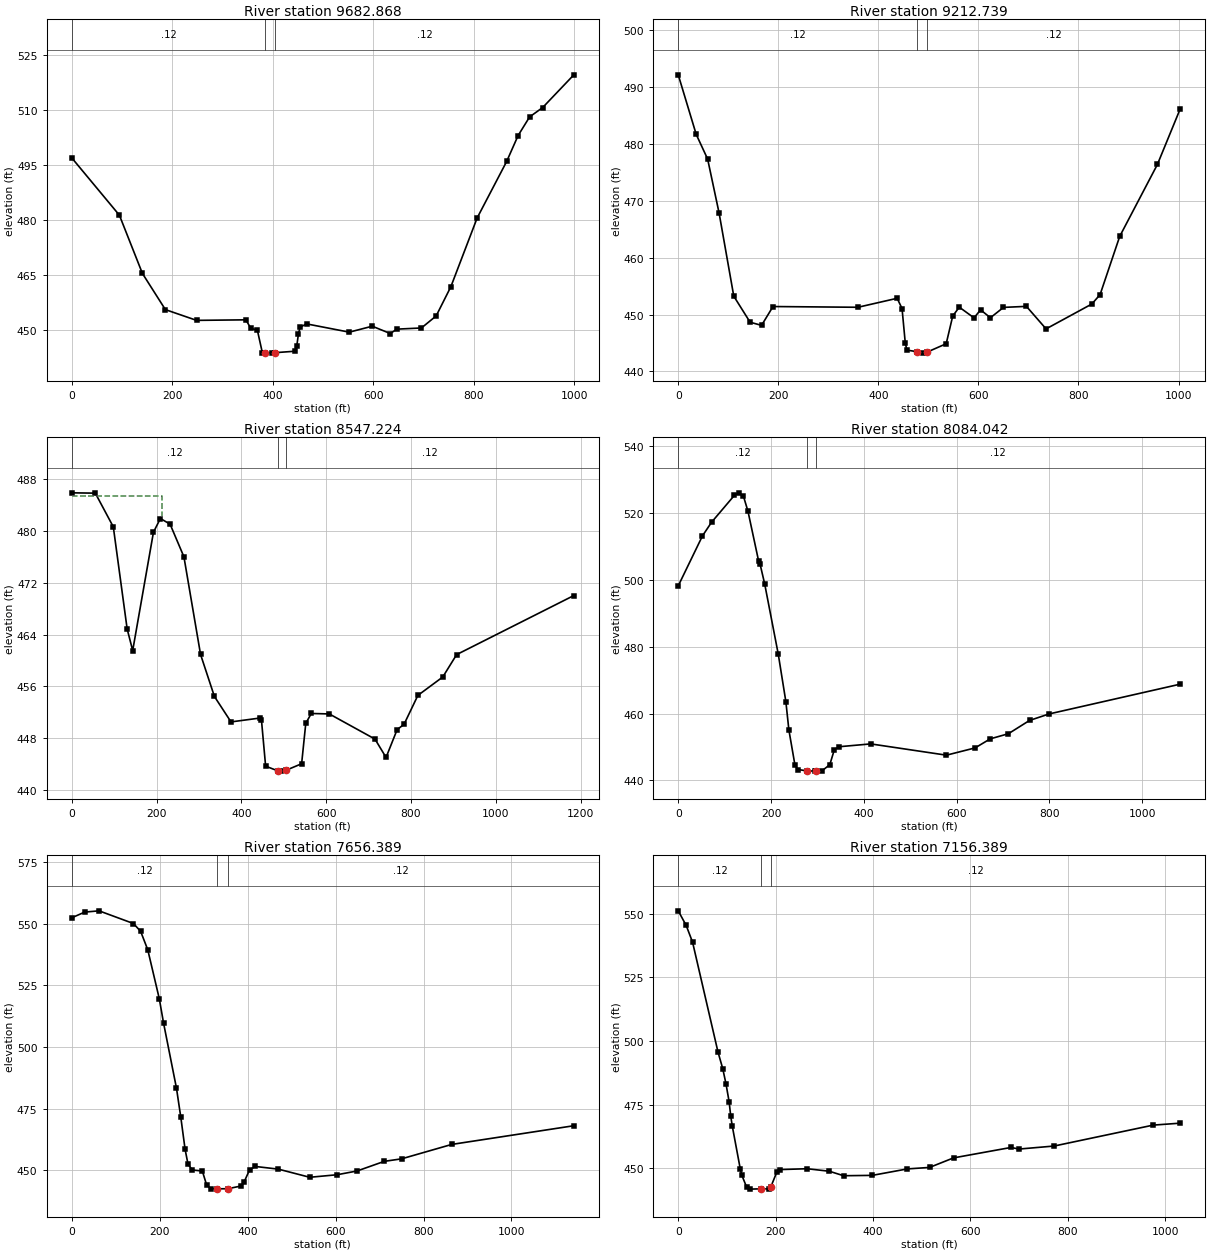
Type RM Length L Ch R = 1 ,9682.868,481.01,470.13,459.16
Node Name=976
XS GIS Cut Line= 3
2384482.45864478 285078.77327019 2384634.3399027285555.203747764
2384785.90521635286030.643413693
#Sta/Elev= 30
       0     497   94.78  481.39  140.54  465.54  186.29  455.68  248.39  452.75
  346.44   452.9  356.25   450.6  369.32  450.07  379.13     444  385.28   443.9
  397.75  443.83  405.27  443.96  444.49  444.35  447.76  445.82  451.03  449.04
   454.3   450.9  467.37  451.79  552.24  449.54   597.9  451.16  633.78  449.17
  646.82  450.36  695.75  450.68   725.1  453.96  754.45  461.95  806.64  480.64
  865.35  496.02  888.18  503.09  911.01  508.15   937.1  510.72  999.07  519.62
#Mann= 3 , 0 , 0
       0     .12       0  385.28    .045       0  405.27     .12       0
Bank Sta=385.28,405.27
XS Rating Curve= 0 ,0
Exp/Cntr=0.3,0.1

Type RM Length L Ch R = 1 ,9212.739,650.47,665.52,675.51
Node Name=977
XS GIS Cut Line= 3
2383882.24199744285284.5451683552384193.58520678285675.292418361
2384507.63510361286069.436315104
#Sta/Elev= 30
       0  492.13   35.92  481.66   58.78  477.32   81.64  467.85  111.03  453.22
  143.68  448.64  166.54  448.09   189.4   451.4   359.2  451.27  437.57  452.85
  447.37  451.05   453.9  444.91  457.17  443.74  477.44  443.46  489.93  443.21
  497.42  443.39  535.61  444.86   548.7  449.74  561.79  451.29  591.25  449.41
  604.34  450.82  623.97  449.43  650.15  451.25  695.97  451.43  735.24  447.47
  826.86  451.85  843.23   453.5   882.5  463.74  957.76  476.37 1003.58  486.19
#Mann= 3 , 0 , 0
       0     .12       0  477.44    .045       0  497.42     .12       0
Bank Sta=477.44,497.42
XS Rating Curve= 0 ,0
Exp/Cntr=0.3,0.1

Type RM Length L Ch R = 1 ,8547.224,477.48,463.18,445.34
Node Name=978
XS GIS Cut Line= 4
2383508.07509486 285501.667109432383673.89562936286119.795466349
2383771.01157686286478.8659424332383942.10277011286496.675618097
#Sta/Elev= 30
       0  485.85   55.51   485.8   97.96   480.6  130.61  464.85  143.67  461.52
  192.65  479.78  208.97  481.89  231.83  481.02  264.48  475.98  303.67  460.93
  336.32  454.45   375.5  450.52  444.07  451.12  447.34  450.79  457.13   443.7
   485.9  442.97  493.05  442.93  505.97  443.08  542.03  444.07  551.82   450.3
  564.88  451.82  607.33  451.75  715.03  447.87  741.13  445.04  767.24  449.33
  783.55  450.15  816.18  454.61  874.91  457.45  907.54   460.9 1183.97  470.01
#Mann= 3 , 0 , 0
       0     .12       0   485.9    .045       0  505.97     .12       0
#XS Ineff= 2 , 0
          211.62  485.43
Permanent Ineff=
       F       F
Bank Sta=485.9,505.97
XS Rating Curve= 0 ,0
Exp/Cntr=0.3,0.1

Type RM Length L Ch R = 1 ,8084.042,445.94,427.65,407.74
Node Name=979
XS GIS Cut Line= 4
2383048.57699811 285979.126456352383420.97290686286350.654256597
2383629.52727978286547.1128531842383899.06184569286556.987505347
#Sta/Elev= 30
       0  498.19   52.28  513.15   71.88  517.22  120.89  525.23  130.69  526.01
  140.49  525.03   150.3  520.51  173.17  505.68  176.43  504.67  186.24  498.84
  215.64  477.75  231.98  463.59  238.51   455.1  251.58  444.61  258.12  443.28
  276.62   442.9  294.06   442.8     297   442.8  310.39  442.95  326.73  444.73
  336.53  449.23  346.33  450.09  414.95  450.94  578.13  447.57  639.99  449.75
  672.55  452.45  711.62  453.98   757.2  457.95  799.52   459.9 1082.26  468.81
#Mann= 3 , 0 , 0
       0     .12       0  276.62    .045       0     297     .12       0
Bank Sta=276.62,297
XS Rating Curve= 0 ,0
Exp/Cntr=0.3,0.1

Type RM Length L Ch R = 1 ,7656.389,518.93,500,480.43
Node Name=980
XS GIS Cut Line= 4
2382775.94073236286491.402990848 2383270.1848226 286612.99559544
2383317.17619844286624.5562678582383900.87024103286593.246947274
#Sta/Elev= 30
       0  552.34   29.36  554.64   61.99  555.16   140.3  550.01  156.61  546.85
  172.92  539.33  199.02  519.57  208.81  509.64  238.18  483.25  247.97  471.54
  257.75  458.49  264.28  452.58  274.07  450.14  296.91  449.74  306.69  444.11
  316.48  442.39  330.61  442.52  354.68  442.55     385  443.65  391.52  445.11
  404.57  450.26  417.63  451.57  469.83  450.49  541.24  447.19  603.09  448.21
  648.81  449.74  710.85  453.65  750.04  454.66  864.33  460.51 1141.91  468.08
#Mann= 3 , 0 , 0
       0     .12       0  330.61    .045       0  354.68     .12       0
Bank Sta=330.61,354.68
XS Rating Curve= 0 ,0
Exp/Cntr=0.3,0.1

Type RM Length L Ch R = 1 ,7156.389,538.08,525.96,511.78
Node Name=981
XS GIS Cut Line= 3
2383000.12269869287109.0858106022383439.16381536286870.710303098
2383906.02377403 286617.23049511
#Sta/Elev= 30
       0  551.11   16.33  545.36   29.39  538.82   81.63  495.68   91.43  489.11
   97.96  483.26  104.49  476.16  107.75  470.54  111.02  466.52  127.34  449.82
  130.61  447.26   140.4  442.66  146.94  441.85  169.81  441.97  186.12  441.91
  190.36  442.87  202.44  448.55  208.97  449.52  264.48  449.86   310.2  448.87
  339.58  447.11  398.36  447.25  470.19  449.78  515.98  450.37  565.16  454.11
  683.22  458.21  699.61  457.58  771.76  458.77  975.07  466.98 1030.81  467.75
#Mann= 3 , 0 , 0
       0     .12       0  169.81    .045       0  190.36     .12       0
Bank Sta=169.81,190.36
XS Rating Curve= 0 ,0
Exp/Cntr=0.3,0.1

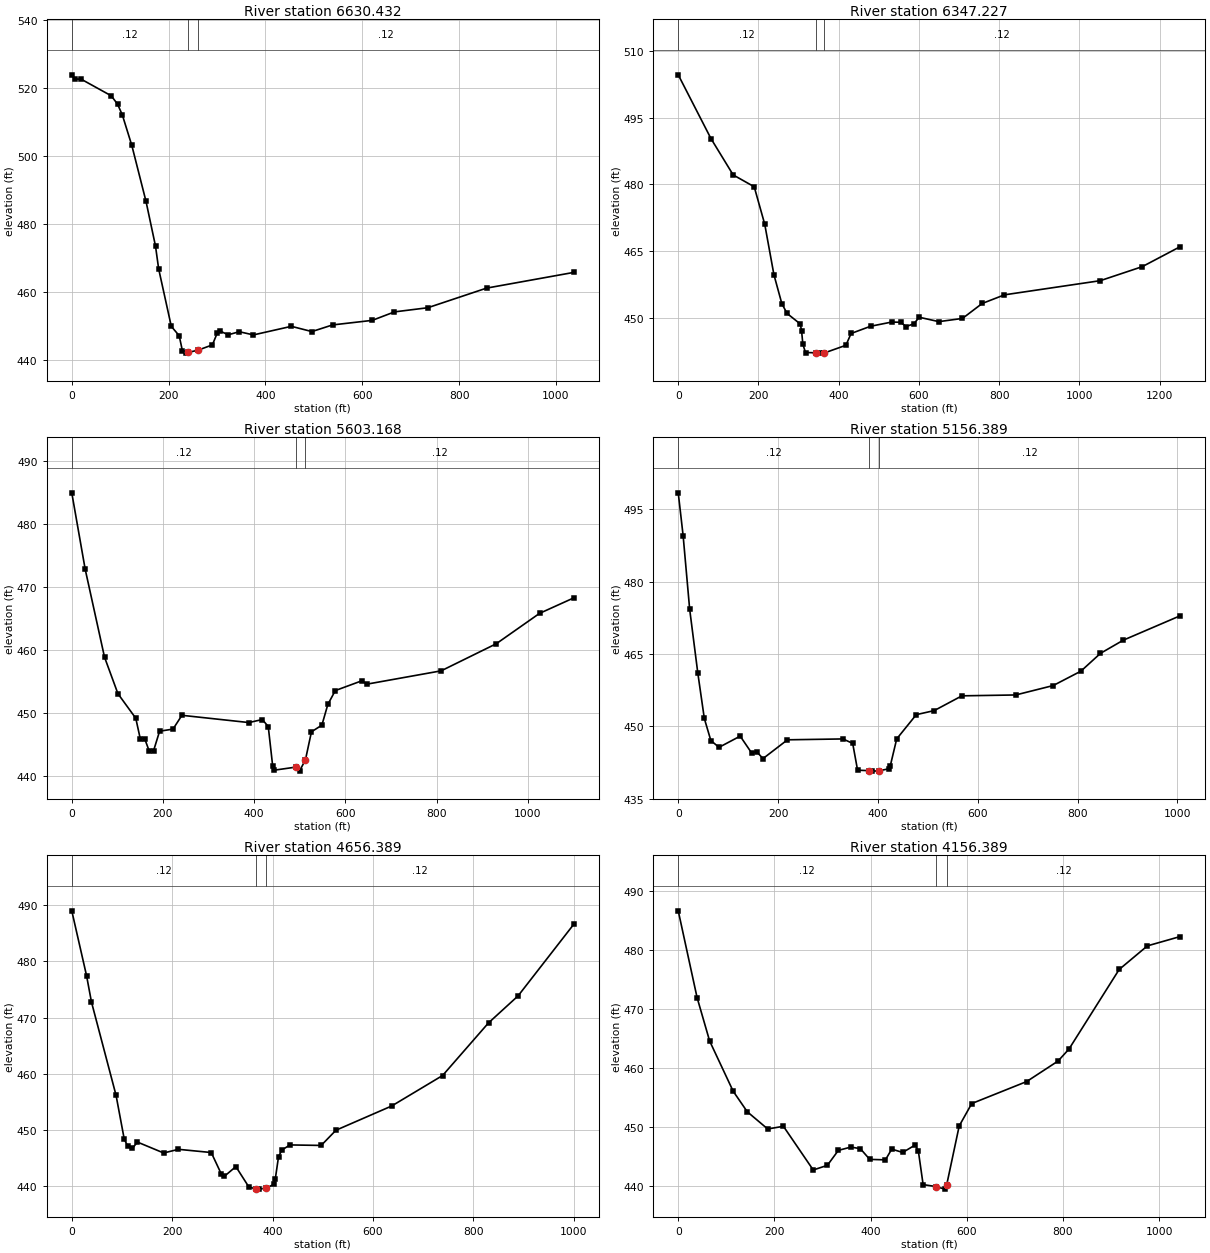
Type RM Length L Ch R = 1 ,6630.432,276.76,283.2,289.06
Node Name=982
XS GIS Cut Line= 3
2383376.21118537287580.3706291912383675.18991812287180.582058683
2383997.21978585286749.970059022
#Sta/Elev= 30
       0  523.77    6.53  522.55   19.58  522.48   81.57  517.61   94.62  515.14
  104.41     512  123.99  503.05  153.35  486.59  172.93  473.47  179.46  466.77
  205.56   449.9  221.87  447.15   228.4  442.78  234.93  442.04  240.91  442.26
  261.03  442.92  290.39  444.46  300.18  447.84  306.71   448.5  323.02  447.42
  345.86  448.33  375.23  447.39  453.54  449.91  495.96  448.37  538.56  450.32
  620.53  451.66  666.43  454.15  735.29  455.37   856.6  461.13 1036.93  465.75
#Mann= 3 , 0 , 0
       0     .12       0  240.91    .045       0  261.03     .12       0
Bank Sta=240.91,261.03
XS Rating Curve= 0 ,0
Exp/Cntr=0.3,0.1

Type RM Length L Ch R = 1 ,6347.227,766.83,744.06,719.07
Node Name=983
XS GIS Cut Line= 5
2383452.01319911287681.1194434322383588.26489511287694.568235442
2383748.75604394287549.5691816062383832.81132202287473.818020776
2384227.07825002286795.139260024
#Sta/Elev= 30
       0  504.71    81.5  490.35  136.91  482.15  189.35  479.48  215.57  471.03
  238.51  459.64  258.17  453.14  271.28  450.92  304.05  448.56  307.33  447.06
   310.6  443.98  317.16  442.12  342.87  442.06  353.21  441.98  363.52     442
  417.86  443.75   430.8  446.41  479.44  448.04  531.77  448.98  554.66  448.94
  567.74  447.97  587.36   448.6  600.44  450.07   649.5  449.08  708.37   449.8
  757.42  453.17  813.02  455.12 1051.75  458.31 1156.41  461.47 1251.25  465.99
#Mann= 3 , 0 , 0
       0     .12       0  342.87    .045       0  363.52     .12       0
Bank Sta=342.87,363.52
XS Rating Curve= 0 ,0
Exp/Cntr=0.3,0.1

Type RM Length L Ch R = 1 ,5603.168,457.82,446.78,435.35
Node Name=984
XS GIS Cut Line= 3
2384377.39619085287940.9929394422384404.34364353287442.298398763
2384439.17493869286841.732670769
#Sta/Elev= 30
       0  484.88   29.38  472.78   71.81  458.83  101.19  453.04  140.36  449.14
  150.15  445.91  159.95  445.89  169.74  443.96  179.53  444.03  192.59  447.09
  221.97  447.42  241.55  449.61  388.44  448.46  417.82  448.94  430.87  447.83
  440.67  441.51  443.93  440.91  492.61  441.41  499.42  440.76   512.5  442.58
  525.58  446.99  548.46  448.05  561.54  451.33  577.89  453.53  636.74   455.1
  646.55  454.54  810.02  456.66  930.99  460.96  1025.8  465.77    1101  468.23
#Mann= 3 , 0 , 0
       0     .12       0  492.61    .045       0   512.5     .12       0
Bank Sta=492.61,512.5
XS Rating Curve= 0 ,0
Exp/Cntr=0.3,0.1

Type RM Length L Ch R = 1 ,5156.389,478.12,500,521.51
Node Name=985
XS GIS Cut Line= 3
2384959.00887278287736.1009607762384800.91141994287255.097985774
2384644.91632511 286780.49165152
#Sta/Elev= 30
       0  498.41     9.8  489.53   22.87  474.32    39.2  461.08   52.27  451.66
   65.33  447.09   81.66  445.68  124.13     448     147  444.52   156.8  444.81
  169.86  443.35  218.86  447.24  329.92  447.42  349.52   446.5  359.32  440.94
  382.17  440.85  388.72  440.75  402.16  440.81  421.39  441.23  424.65  441.77
  437.72  447.43  476.92  452.45  512.85  453.29  568.36  456.35  676.11  456.53
  751.21  458.48  806.72  461.46  845.91  465.15  891.62  467.88  1005.9  472.95
#Mann= 3 , 0 , 0
       0     .12       0  382.17    .045       0  402.16     .12       0
Bank Sta=382.17,402.16
XS Rating Curve= 0 ,0
Exp/Cntr=0.3,0.1

Type RM Length L Ch R = 1 ,4656.389,480.76,500,519.04
Node Name=986
XS GIS Cut Line= 3
2385174.09702528287743.4979276062385371.36926852287284.009673357
2385568.61985828 286824.57161586
#Sta/Elev= 30
       0  488.95   29.41  477.45   39.22  472.76   88.24  456.17  104.58  448.37
  111.12  447.23  120.93  446.78  130.73  447.88  183.02  445.94  212.44  446.59
   277.8  446.02  297.41  442.29  303.95   441.8  326.83  443.52  352.97  439.87
  367.42  439.56  372.56  439.52  387.39   439.7     402  440.35  405.27  441.26
   411.8  445.26  418.34  446.46  434.68  447.37  496.78  447.28  526.19  449.98
   637.3  454.29   738.6   459.7  830.11  469.05  888.93  473.84 1000.04  486.58
#Mann= 3 , 0 , 0
       0     .12       0  367.42    .045       0  387.39     .12       0
Bank Sta=367.42,387.39
XS Rating Curve= 0 ,0
Exp/Cntr=0.3,0.1

Type RM Length L Ch R = 1 ,4156.389,614.72,635.3,636.79
Node Name=987
XS GIS Cut Line= 3
2385254.49220569287933.8866544372385725.67269377287659.519749105
2386156.89460036287408.420841858
#Sta/Elev= 30
       0  486.66   39.18  471.94    65.3  464.56  114.27  456.03  143.66  452.54
   186.1  449.62  218.75  450.08  280.78  442.66  310.17  443.45  333.02  445.99
  359.14  446.55  378.73  446.28  398.32  444.46  430.97  444.38  444.03   446.2
  466.88  445.64     493  446.91  499.53  445.81  509.33  440.18  535.45  439.85
  555.03  439.41  558.29  440.11  584.38  450.14  610.47  453.94  724.62  457.67
  789.85  461.15  812.68  463.19  917.05   476.7  975.76  480.71 1044.25   482.3
#Mann= 3 , 0 , 0
       0     .12       0  535.45    .045       0  558.29     .12       0
Bank Sta=535.45,558.29
XS Rating Curve= 0 ,0
Exp/Cntr=0.3,0.1

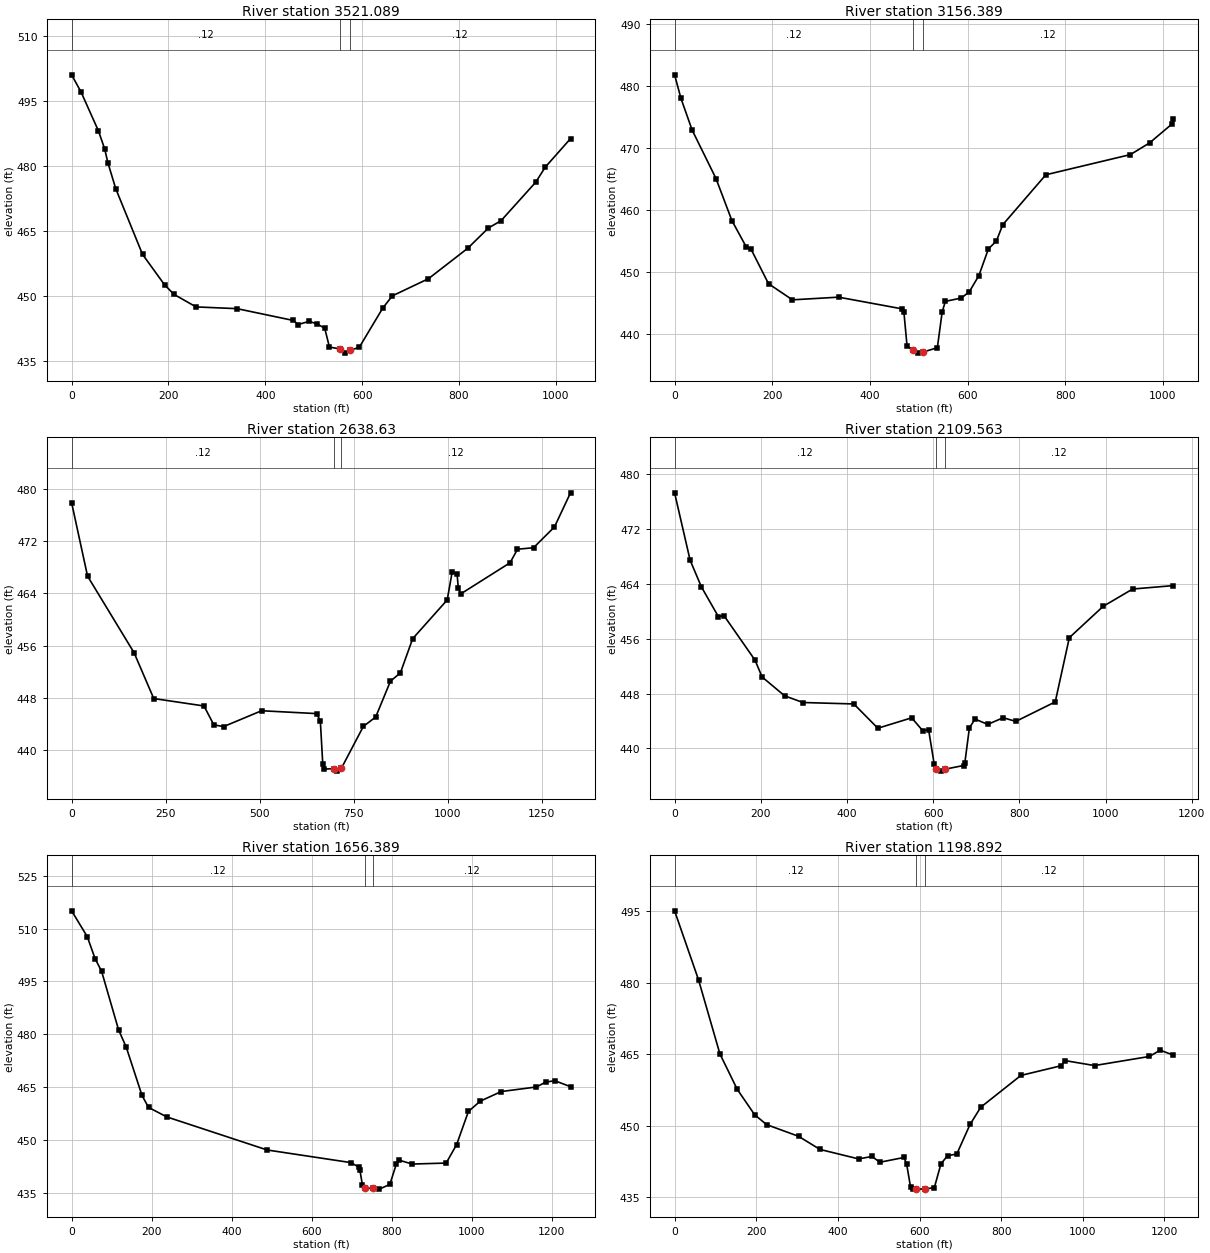
Type RM Length L Ch R = 1 ,3521.089,349.01,364.7,369.31
Node Name=988
XS GIS Cut Line= 5
2385305.76670945288283.4318871052385686.16391453288269.135327771
2385864.35351877288223.1029395162386094.49741544288165.315653518
2386322.24433528288181.760830596
#Sta/Elev= 30
       0  501.12   19.52  497.15   55.31  488.21   68.32  484.02   74.83  480.88
    91.1  474.87  146.41  459.71  191.96  452.68  211.48  450.47  257.03  447.58
  341.62  447.18  458.16  444.45  467.84  443.52  490.44  444.24  506.59  443.68
  522.73  442.66  532.42  438.32  554.39  437.89   564.7  436.92  574.23  437.57
  593.96  438.24  642.72  447.33  662.22  450.12  736.98  454.09   818.3  461.13
  860.71  465.78   886.8  467.46  958.57  476.36  978.14  479.82 1030.33   486.4
#Mann= 3 , 0 , 0
       0     .12       0  554.39    .045       0  574.23     .12       0
Bank Sta=554.39,574.23
XS Rating Curve= 0 ,0
Exp/Cntr=0.3,0.1

Type RM Length L Ch R = 1 ,3156.389,530.6,517.76,499.48
Node Name=989
XS GIS Cut Line= 3
2385357.31549086 288529.656460272385855.02840619288563.382114604
2386376.53983036288598.719970435
#Sta/Elev= 30
       0  481.78   13.04  477.99   35.87   472.9   84.77  465.09  117.38  458.31
  146.72  454.08   156.5  453.72  192.37  448.15  241.28  445.56  335.83  445.99
  466.25   444.1  469.51  443.62  476.03  438.09  488.82  437.46  498.85  436.98
  508.88  437.15  538.06  437.86  547.86  443.58  554.39  445.31  587.06  445.85
   603.4  446.85     623  449.45   642.6  453.76  658.93  455.03     672  457.65
  760.21  465.69  933.35  468.94  972.56  470.82 1018.29  473.85 1021.56  474.61
#Mann= 3 , 0 , 0
       0     .12       0  488.82    .045       0  508.88     .12       0
Bank Sta=488.82,508.88
XS Rating Curve= 0 ,0
Exp/Cntr=0.3,0.1

Type RM Length L Ch R = 1 ,2638.63 ,496.21,529.07,554.72
Node Name=990
XS GIS Cut Line= 4
2385219.55625194289067.950659275 2385605.4793646289187.959277526
2385871.77738844 289044.030103432386427.49182819288769.964050516
#Sta/Elev= 30
       0  477.88   42.37  466.63  166.22  454.88  218.37  447.88     352  446.74
  378.08  443.85  404.15  443.58  505.05  446.01  651.52  445.57  661.29  444.44
   667.8  437.83  671.05  437.07  696.77  437.14  706.86  436.76  717.21  437.19
   775.7  443.61  808.49  445.05  847.83  450.55  874.06   451.8  906.84  457.05
  998.64  462.98 1011.75  467.24 1024.86  466.96 1028.14  464.81  1034.7  463.91
 1165.84  468.68 1185.51  470.75 1228.13  470.98 1283.86  474.17 1326.48  479.39
#Mann= 3 , 0 , 0
       0     .12       0  696.77    .045       0  717.21     .12       0
Bank Sta=696.77,717.21
XS Rating Curve= 0 ,0
Exp/Cntr=0.3,0.1

Type RM Length L Ch R = 1 ,2109.563,465.33,453.17,439.64
Node Name=991
XS GIS Cut Line= 3
2385213.27181569289102.7996709352385657.10754219289381.447407603
2386197.22555645289712.759080932
#Sta/Elev= 30
       0  477.26   36.03  467.44   62.23  463.55  101.54  459.23  114.64  459.36
  186.69  452.87  203.07  450.42  255.48  447.67  298.06   446.7  415.97  446.49
  471.65  442.95  550.18  444.47  576.31  442.55  589.38  442.76  602.44  437.71
  606.98  436.98  618.84   436.7  626.51  436.97  670.57  437.52  673.61  437.95
   684.1     443  697.16  444.29  726.56  443.51  762.49  444.48  791.88  443.95
  883.33  446.79     916  456.15  994.38  460.71 1062.97  463.24 1157.69  463.74
#Mann= 3 , 0 , 0
       0     .12       0  606.98    .045       0  626.51     .12       0
Bank Sta=606.98,626.51
XS Rating Curve= 0 ,0
Exp/Cntr=0.3,0.1

Type RM Length L Ch R = 1 ,1656.389,446.61,457.5,463.36
Node Name=992
XS GIS Cut Line= 4
2384972.64500035289627.1519686882385157.71713677289786.587345347
2385652.21122652289851.740430266 2386151.6557657 289917.54607293
#Sta/Elev= 30
       0  515.09   39.08  507.76   58.63   501.5   74.91  497.91  117.25   481.3
   136.8  476.23  175.88  462.61  192.16   459.2  237.76   456.5  488.77  447.09
  697.41  443.51  716.97  442.28  720.23   441.5  726.75  437.15  733.15  436.32
  753.04  436.16  769.21  435.96  795.38  437.32  811.74  443.18  818.28  444.21
  850.99  443.09  936.05  443.37  962.21  448.63  991.66  458.05  1021.1  460.96
 1073.43   463.7 1161.76  465.01 1184.65  466.38 1207.55  466.79 1246.81  465.08
#Mann= 3 , 0 , 0
       0     .12       0  733.15    .045       0  753.04     .12       0
Bank Sta=733.15,753.04
XS Rating Curve= 0 ,0
Exp/Cntr=0.3,0.1

Type RM Length L Ch R = 1 ,1198.892,702.57,658.14,611.1
Node Name=993
XS GIS Cut Line= 4
2384954.16997169290011.3700322662385487.95827419  290241.6563171
2385609.66997303  290294.08337762386012.15604469289983.847121432
#Sta/Elev= 30
       0  495.05   58.79  480.54  111.04  465.03   153.5   457.6  195.96  452.29
  225.35   450.2  303.74  447.75  355.99     445  450.71  443.01  483.37  443.52
  502.96  442.31  561.75  443.31  568.28  441.98  578.08  437.07  584.58  436.67
  592.39  436.68  612.97   436.7  636.29  436.99  652.45  441.97  668.62  443.68
  691.24  444.03   723.7  450.23  749.93  453.85  848.29  460.52  946.64  462.55
  956.48  463.63 1028.61  462.59 1163.03   464.5 1189.26  465.81 1222.04  464.78
#Mann= 3 , 0 , 0
       0     .12       0  592.39    .045       0  612.97     .12       0
Bank Sta=592.39,612.97
XS Rating Curve= 0 ,0
Exp/Cntr=0.3,0.1

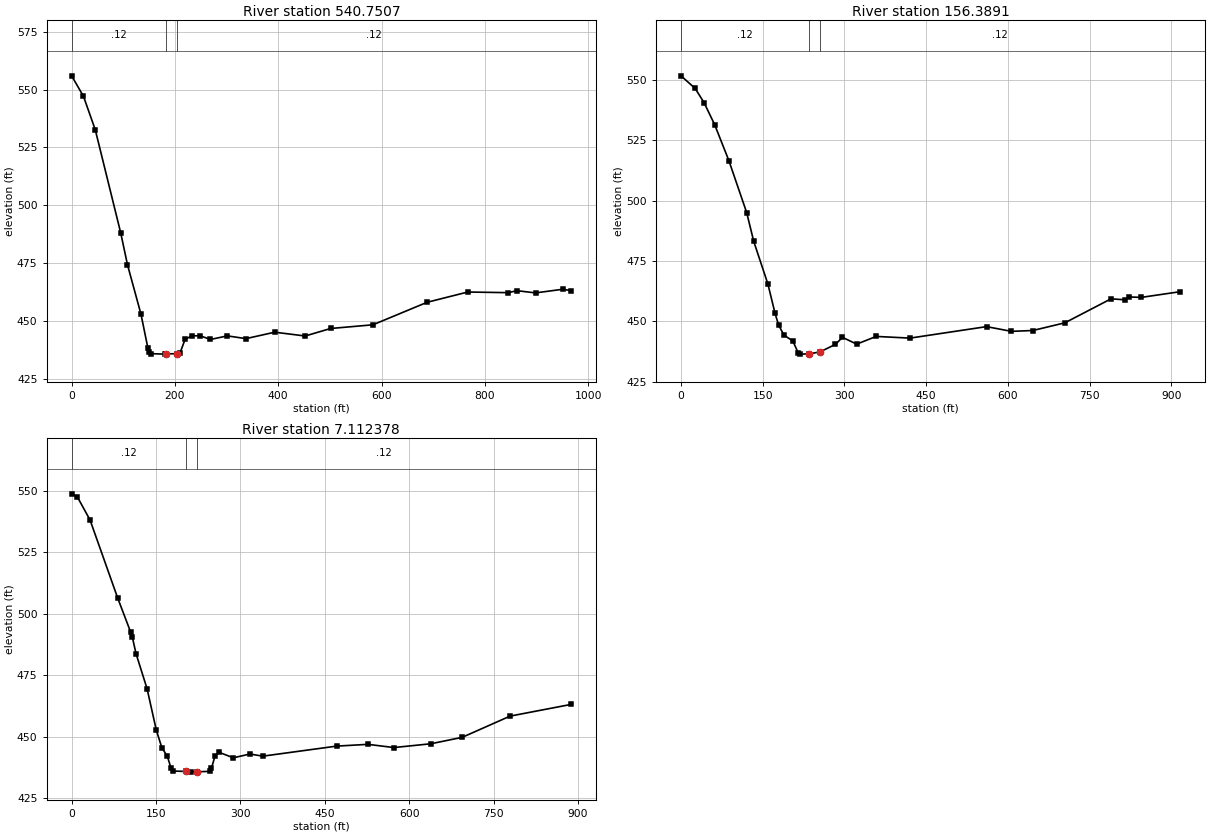
Type RM Length L Ch R = 1 ,540.7507,382.17,384.36,385.1
Node Name=994
XS GIS Cut Line= 3
2385469.53869161290872.3532184362385707.15206152290393.939149022
2385993.05897002290068.916505098
#Sta/Elev= 30
       0  555.92   22.94  547.06   45.88   532.5   95.04     488  108.15  474.23
  134.36  452.78  147.47  438.41  150.75  436.39  154.03  435.81  180.24  435.61
  183.66  435.72   204.1   435.8  209.74  436.04  219.57  441.95  232.68  443.52
  249.06  443.54  268.73  441.94   301.5   443.5  337.54  442.31  393.26  445.09
  452.24  443.45   501.4  446.69  583.36  448.29   688.3  458.02  767.01  462.46
  845.71  462.18  862.11  463.05  898.18  462.08  950.65  463.64  967.05  463.08
#Mann= 3 , 0 , 0
       0     .12       0  183.66    .045       0   204.1     .12       0
Bank Sta=183.66,204.1
XS Rating Curve= 0 ,0
Exp/Cntr=0.3,0.1

Type RM Length L Ch R = 1 ,156.3891,172.07,149.28,126.99
Node Name=995
XS GIS Cut Line= 3
 2385802.0990501290975.4740751832385971.88119085290670.995681524
2386055.55884503290108.846871436
#Sta/Elev= 30
       0  551.78   26.06  546.53   42.36  540.65    61.9  531.48   87.97  516.58
  120.55   495.1  133.58  483.11  159.65  465.39  172.68  453.28   179.2  448.48
  188.97   444.3  205.26  441.89  215.03  437.01  218.29  436.42  235.25  436.52
  255.15  437.34  283.45  440.46  296.49  443.37  322.55  440.56  358.42  443.76
  420.48  443.06  560.93  447.82  606.66  445.86  645.85  446.21  704.65  449.39
  789.57  459.35   815.7  458.93  822.23  460.12   845.1  459.94  916.96  462.32
#Mann= 3 , 0 , 0
       0     .12       0  235.25    .045       0  255.15     .12       0
Bank Sta=235.25,255.15
XS Rating Curve= 0 ,0
Exp/Cntr=0.3,0.1

Type RM Length L Ch R = 1 ,7.112378,18.8,7.11,6.09
Node Name=996
XS GIS Cut Line= 4
2386116.68601936 290972.308727192386063.12116586 290766.57324627
2386044.05919611290684.2804318522386151.04487452290103.638548523
#Sta/Elev= 30
       0   548.8    9.81  547.69   32.71  538.15   81.77  506.42  104.66  492.64
  107.93  490.38  114.47  483.71   134.1  469.42  150.45  452.61  160.26  445.49
  170.08  441.94  176.62  437.16  179.89  435.96  203.16  435.81  211.83  435.52
  222.25  435.68  245.08  435.81  248.33  437.02  254.83  442.11  261.33  443.64
  287.32  441.35  316.75  442.89  339.71  442.02  470.91  446.11  526.67  446.83
  572.59  445.52  638.19  447.06  693.96  449.68  779.24  458.33  887.48  463.08
#Mann= 3 , 0 , 0
       0     .12       0  203.16    .045       0  222.25     .12       0
Bank Sta=203.16,222.25
XS Rating Curve= 0 ,0
Exp/Cntr=0.3,0.1

Chan Stop Cuts=-1
Use User Specified Reach Order=0
Composite Channel Slope=5